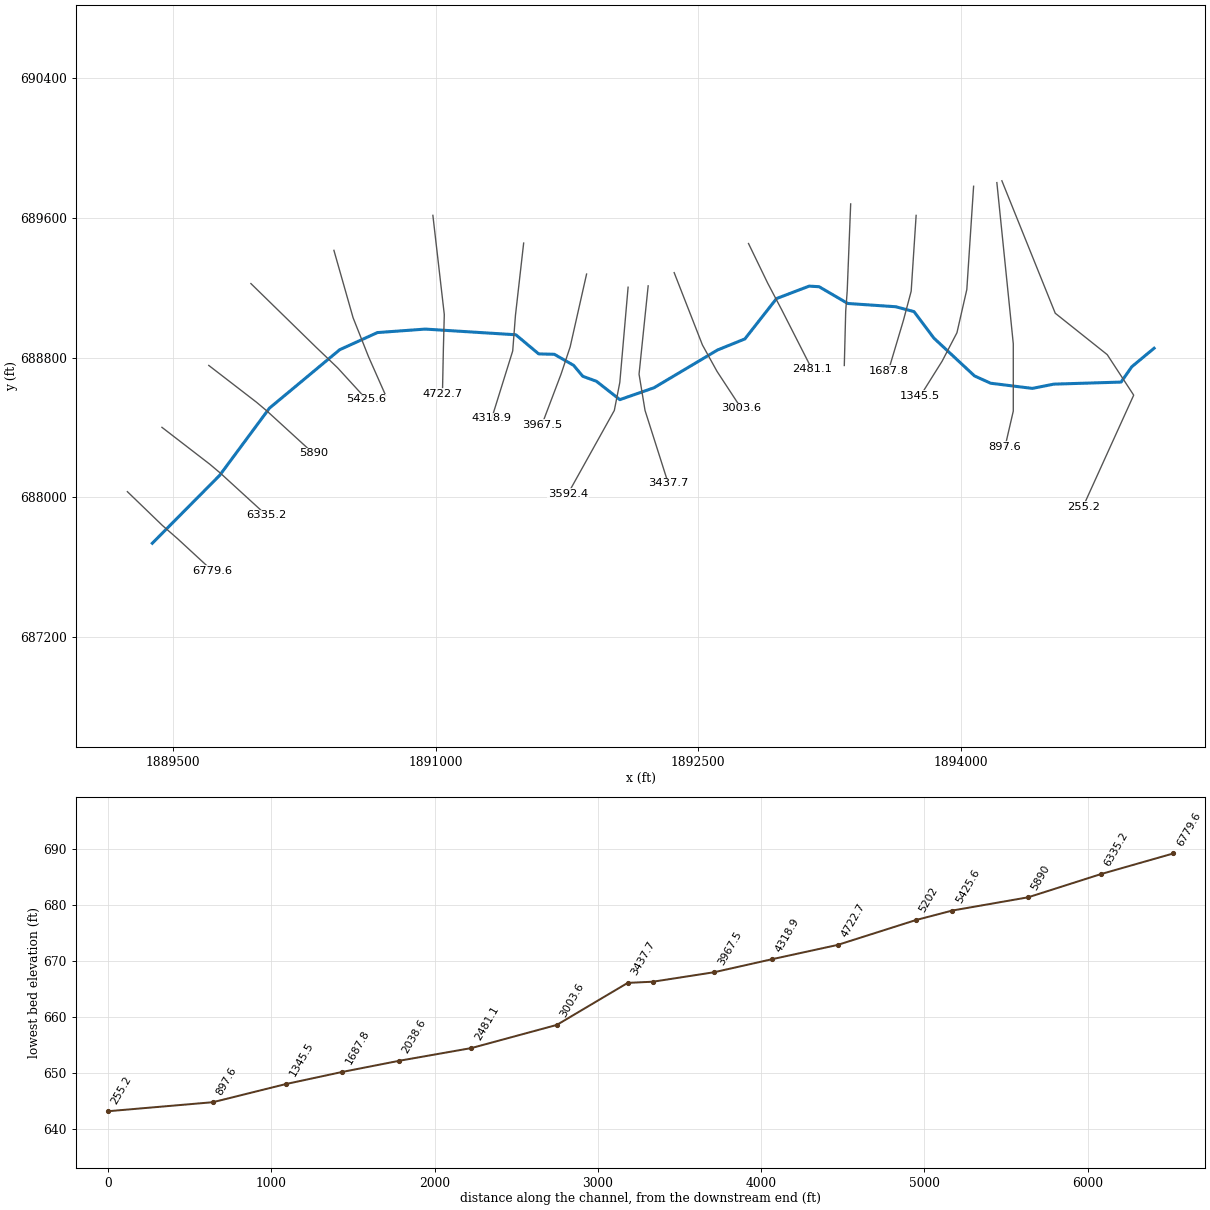
--- BarnesRun.prj (project) ---

Proj Title=BarnesRun
Current Plan=p01
Default Exp/Contr=0,0
English Units
Geom File=g01
Flow File=f01
Plan File=p01
BEGIN DESCRIPTION:
AMEC Environment & Infrastructure, 2013
Projection: NAD 1983 State Plane West Virginia South FIPS 4702 (US Feet)
Vertical Datum: NAVD 1988
END DESCRIPTION:
DSS Export Rating Curves= 0
DSS Export Rating Curve Sorted= 0
DSS Export Volume Flow Curves= 0
DXF OffsetX= 0
DXF OffsetY= 0
DXF ScaleX= 0
DXF ScaleY= 0

--- BarnesRun.p01 (plan) ---

Plan Title=Floodplain
Program Version=4.00
Geom File=g01
Flow File=f01
K Sum by GR=0
Std Step Tol=0.01
Critical Tol=0.01
Num of Std Step Trials=20
Max Error Tol=0.3
Flow Tol Ratio=0.001
Split Flow NTrial=30
Split Flow Tol=0.02
Split Flow Ratio=0.02
Log Output Level=0
Friction Slope Method=1
Unsteady Friction Slope Method=2
Unsteady Bridges Friction Slope Method=1
Global Log Level=0
CheckData=False
Run HTab=0
Run UNet=0
Run PostProcess=0
UNET Theta=0
UNET Theta Warmup=0
UNET ZTol=0
UNET ZSATol=0
UNET MxIter=0
UNET MaxInSteps=0
UNET DtIC=0
UNET DtMin=0
UNET MaxCRTS=0
UNET WFStab=0
UNET SFStab=0
UNET WFX=0
UNET SFX=0
UNET DSS MLevel=0
UNET DZMax Abort=0
UNET Convert EG Bridges=0
UNET Use Existing IB Tables=0
UNET Froude Limit=0
UNET Froude Power=0
Write IC File=0
Echo Input=False
Echo Output=False
Write Detailed=0

--- BarnesRun.f01 (steady flow) ---

Flow Title=NFF Regression Equation
Program Version=4.10
Number of Profiles= 1
Profile Names=P100yr
River Rch & RM=BarnesRun,Main            ,6779.6
 1032.92
River Rch & RM=BarnesRun,Main            ,3592.4
 1104.15
River Rch & RM=BarnesRun,Main            ,3437.7
1227.602
River Rch & RM=BarnesRun,Main            ,255.2
1278.331
Boundary for River Rch & Prof#=BarnesRun,Main            , 1
Up Type= 0
Dn Type= 3
Dn Slope=0.0025
DSS Import GetInterval= 0
DSS Import GetPeak= 0
DSS Import FillOption= 0

--- BarnesRun.g01 (geometry) ---

Geom Title=USGS 3m DEM
Program Version=4.10

River Reach=BarnesRun       ,Main
Reach XY= 30
     1889382.859      687737.815     1889767.527      688126.492
     1890051.489       688510.72     1890452.734      688845.109
     1890668.032      688943.211     1890941.032      688963.094
     1891458.227      688930.637     1891588.848      688821.155
     1891677.846      688818.958     1891788.274      688755.688
     1891840.381      688693.166     1891918.787      688664.388
     1892052.277      688559.442     1892246.795      688627.186
     1892609.313      688843.212     1892766.084      688906.834
     1892946.701      689137.836     1893132.996      689208.962
      1893189.85      689205.582     1893353.417      689109.658
     1893627.528      689090.972     1893731.733      689063.074
     1893844.636      688912.092     1894077.376      688695.002
     1894169.428      688653.323     1894407.371      688623.808
      1894529.69      688648.129     1894913.994      688659.967
      1894975.25       688747.86     1895102.463      688853.462

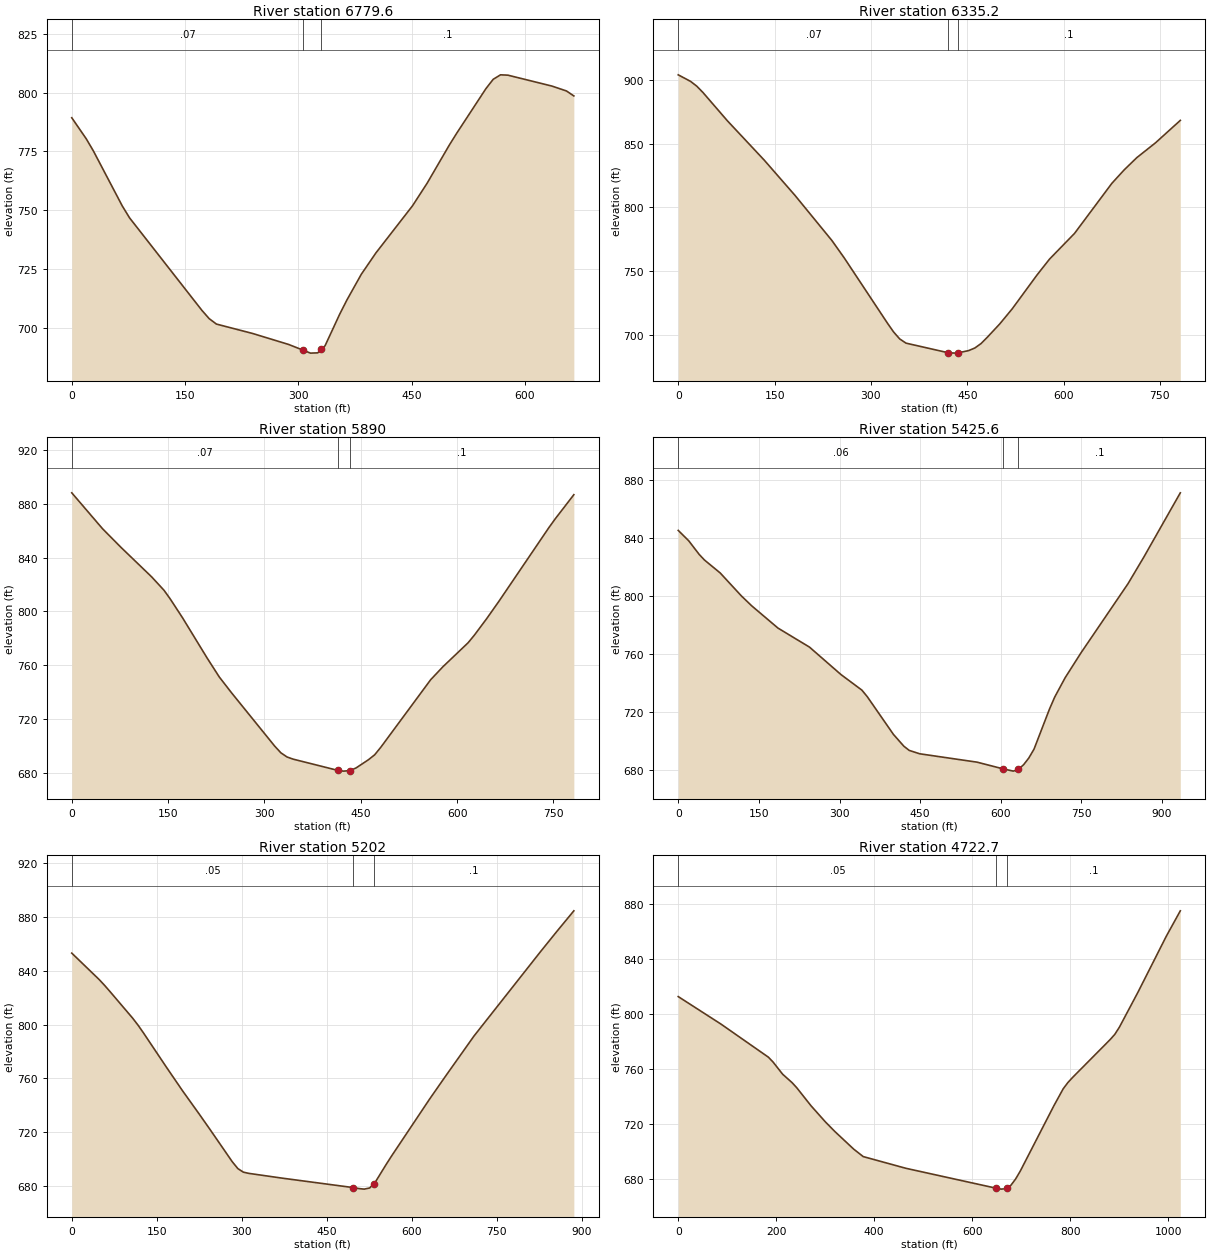
Type RM Length L Ch R = 1 ,6779.6  ,444.2,444.5,443.8
XS GIS Cut Line= 4
     1889240.411      688033.005     1889440.064      687839.863
      1889526.87      687763.908     1889726.522      687579.446
#Sta/Elev= 30
       0  789.27    19.2  780.31    28.7  775.12      67  751.71    76.6  746.68
   172.4  707.36     182  703.85   191.6  701.54   239.5  697.55   287.4  692.86
   306.6  690.42   316.2  689.19   325.8  689.31   330.4  690.74   335.5  692.33
   354.7  705.63   364.3  711.71   383.5  722.72   402.8  731.78   451.4  751.87
   470.8   761.5   499.9  777.56   509.6  782.56   548.5  801.62   558.2  805.62
   567.9  807.52   577.6  807.38   635.8  802.75   655.2  800.66     665  798.55
#Mann= 3 , 0 , 0
       0     .07       0   306.6    .045       0   330.4      .1       0
Bank Sta=306.6,330.4
XS Rating Curve= 0 ,0
Exp/Cntr=0.3,0.1

Type RM Length L Ch R = 1 ,6335.2  ,444.9,445.2,445.2
XS GIS Cut Line= 4
     1889437.785      688400.988     1889710.642      688190.224
     1889770.512      688139.745     1890035.008      687897.516
#Sta/Elev= 30
       0  904.23    19.2  899.08    28.7  895.39    38.3  890.46    76.6  868.07
   134.1  837.07     182  809.35   239.4  773.92   258.6  760.22   325.6  709.15
   335.2   702.2   344.8  696.67   354.6  693.35   420.7  685.75   432.8   685.5
   435.7   685.7   452.2   687.5   461.9  689.55   471.6  693.08   481.2  697.97
   500.6  708.46     520  720.32   558.8  747.05   578.2  759.45     617  779.59
   675.1  818.92   694.5  829.62   713.9  839.11     743  850.76   781.7  868.42
#Mann= 3 , 0 , 0
       0     .07       0   420.7    .045       0   435.7      .1       0
Bank Sta=420.7,435.7
XS Rating Curve= 0 ,0
Exp/Cntr=0.3,0.1

Type RM Length L Ch R = 1 ,5890    ,465.6,464.4,463.6
XS GIS Cut Line= 4
     1889705.146      688755.155     1889978.003       688544.39
     1890037.873      688493.912     1890302.369      688251.683
#Sta/Elev= 30
       0  888.18    47.9   861.5    76.6  847.67   124.5  825.67   143.7  815.72
   153.2  809.39   172.4  795.37   210.7  765.45   229.8  751.25     249  739.44
     316  699.93   325.6  694.96   335.2  691.87   344.8  690.25   414.1  681.94
   423.1  681.37   432.8  681.74   442.5  683.69   461.9  689.84   471.6   693.5
   481.2  699.13   558.8   749.3   578.2   759.1     617  776.72   626.6  782.28
     646  794.68   665.4  807.82     743  862.43   752.7  868.84   781.7  886.79
#Mann= 3 , 0 , 0
       0     .07       0   414.1    .045       0   432.8      .1       0
Bank Sta=414.1,432.8
XS Rating Curve= 0 ,0
Exp/Cntr=0.3,0.1

Type RM Length L Ch R = 1 ,5425.6  ,232.8,223.6,213.4
XS GIS Cut Line= 4
     1889945.706      689223.543     1890315.498      688861.564
     1890440.498      688741.773     1890604.561      688562.085
#Sta/Elev= 30
       0  845.32    19.5  838.15      39  828.72    48.8  824.86    78.1  815.91
   117.2  800.16   136.7   793.2   185.5  777.84   244.1   764.7   302.7  745.73
   341.7  734.94   351.5  730.51   400.3  704.38   419.8  696.18   429.6  693.34
   449.1  690.99   555.9   685.2     604   680.6   623.3  679.01   632.9  680.26
   642.5  683.47   652.1  688.07   661.8   694.2   690.6   721.9   700.3   730.2
   719.8  743.61     749  760.64   836.6  808.49   865.8  826.73   933.9  871.28
#Mann= 3 , 0 , 0
       0     .06       0     604    .045       0   632.9      .1       0
Bank Sta=604,632.9
XS Rating Curve= 0 ,0
Exp/Cntr=0.3,0.1

Type RM Length L Ch R = 1 ,5202    ,488.4,479.3,470.2
XS GIS Cut Line= 4
     1890419.665      689413.648      1890529.04      689028.231
     1890617.581      688804.273      1890716.54      688580.314
#Sta/Elev= 30
       0   853.2    48.9  833.29    58.6  828.86    68.4   824.1   107.5  804.71
   117.3  799.34     127  793.46   166.1  768.81   195.4  750.69   224.8  733.36
   244.3  721.62   283.4  697.68   293.2   692.6   302.9  689.96   312.7  689.04
   371.3   685.5     497  678.45   506.6  677.74   516.2  677.31   525.9  678.17
   532.7  681.11   535.5  682.32   554.8  695.58   564.4  701.91   631.8   744.5
     661   762.2     710  791.39   827.5   854.3   856.9  869.68   886.3  884.72
#Mann= 3 , 0 , 0
       0     .05       0     497    .045       0   532.7      .1       0
Bank Sta=497,532.7
XS Rating Curve= 0 ,0
Exp/Cntr=0.3,0.1

Type RM Length L Ch R = 1 ,4722.7  ,404.6,403.9,402.2
XS GIS Cut Line= 4
      1890984.66      689613.951     1891049.873       689046.46
     1891044.665      688851.148     1891039.348      688593.118
#Sta/Elev= 30
       0   812.7    87.1  792.76     184   768.7   193.6  765.14     213  756.37
   232.4  750.19     242  746.46   271.1  733.38   300.1   721.8   319.5  714.77
   358.2   701.9   377.6   696.5   464.7     688   649.4   673.5   659.2  672.88
   668.9  673.25     672  673.99   678.7  675.58   688.5   680.2   698.2  686.06
   766.6  733.38   785.7  745.75   795.3  750.29   804.8  753.96   881.3   781.4
   890.9  785.23   900.4  790.49   938.7  816.17     996  856.46  1024.7  874.98
#Mann= 3 , 0 , 0
       0     .05       0   649.4    .045       0     672      .1       0
Bank Sta=649.4,672
XS Rating Curve= 0 ,0
Exp/Cntr=0.3,0.1

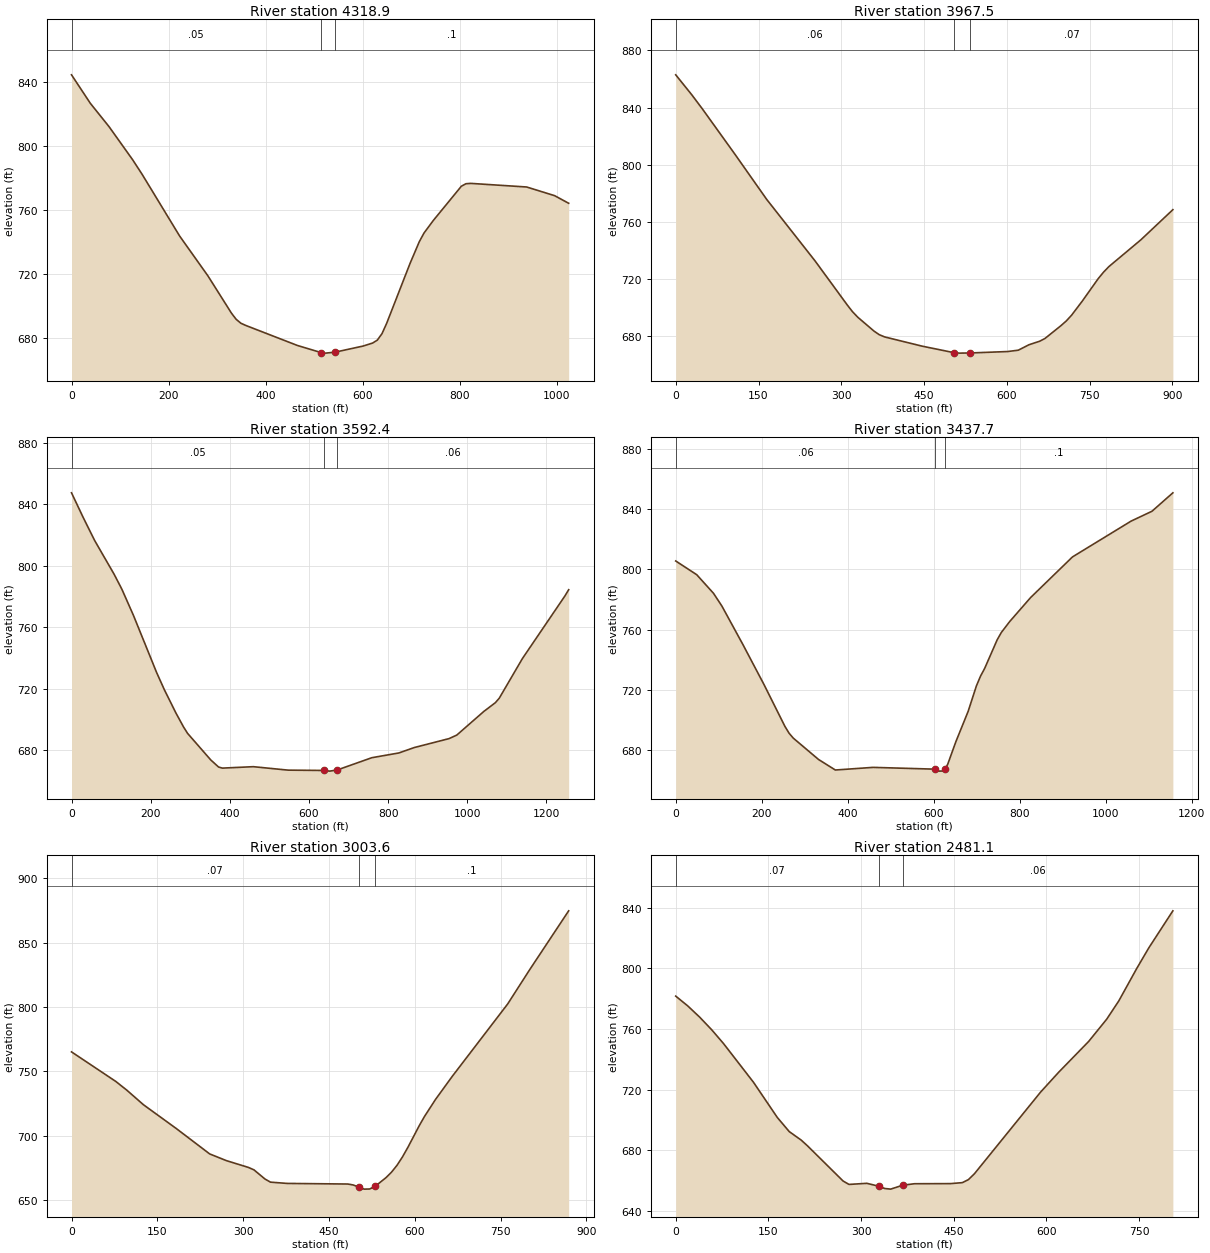
Type RM Length L Ch R = 1 ,4318.9  ,355.4,351.3,346.5
XS GIS Cut Line= 4
     1891502.998      689455.314     1891456.123      689041.252
     1891440.498      688838.127     1891320.598      688452.493
#Sta/Elev= 30
       0  844.72    38.8  826.85    77.5  812.17     126  791.46   145.4   782.4
   222.9  743.63     281  718.75   329.5  695.38   339.2  691.52   348.9  689.07
   358.6  687.72   465.2  675.14   513.7  670.71   523.4  670.32   542.8  670.91
     601  674.77   620.4  676.65     630  678.45   639.7  682.53   649.3  688.99
   697.4  726.49   716.6  740.18   726.2  745.56   745.4  753.45   803.1  774.88
   812.7  776.48   822.4  776.69   937.7  774.43   995.4  768.99  1024.3  764.23
#Mann= 3 , 0 , 0
       0     .05       0   513.7    .045       0   542.8      .1       0
Bank Sta=513.7,542.8
XS Rating Curve= 0 ,0
Exp/Cntr=0.3,0.1

Type RM Length L Ch R = 1 ,3967.5  ,372.2,375.1,376.9
XS GIS Cut Line= 4
     1891862.265      689278.014     1891768.515      688861.347
     1891716.431      688705.097     1891607.056      688416.035
#Sta/Elev= 30
       0  862.91    29.1  848.93    48.5  838.94   106.8  807.57     165  775.59
   252.4  732.64   310.6  701.86   320.3  697.04     330  693.12   359.1   683.5
   368.8  680.93   378.6  679.36   446.5   672.9   504.6  668.31   514.3  668.02
   533.7  668.13   601.4  669.13   620.8  670.08   640.1   673.9   659.4  676.35
     669  678.26     698  687.25   707.7  690.57   717.3  694.59   736.7  704.48
   765.6  720.22   775.3  724.77     785  728.66   842.9   747.4   900.8  768.48
#Mann= 3 , 0 , 0
       0     .06       0   504.6    .045       0   533.7     .07       0
Bank Sta=504.6,533.7
XS Rating Curve= 0 ,0
Exp/Cntr=0.3,0.1

Type RM Length L Ch R = 1 ,3592.4  ,146.7,154.7,162.8
XS GIS Cut Line= 4
     1892099.352       689202.71     1892051.935      688657.354
     1892020.685      688497.632     1891755.494      688020.201
#Sta/Elev= 30
       0  847.34    29.3  831.41    58.6  816.26   107.5  794.46   127.1  784.73
   156.4  767.68   215.1  730.43   234.6  719.28   263.9  704.09   283.5  694.87
   293.3  690.88   351.9   673.6   371.5  669.01   381.2  668.29   459.4  669.22
   547.4  666.97   637.2  666.77   652.7  666.33   671.9  667.13   758.9  675.06
   827.2  678.15   866.2  681.67     954  687.48   973.5  689.76  1041.8  705.13
    1071  710.85  1080.8  713.73  1139.3  739.51  1246.6  780.19  1256.3  784.32
#Mann= 3 , 0 , 0
       0     .05       0   637.2    .045       0   671.9     .06       0
Bank Sta=637.2,671.9
XS Rating Curve= 0 ,0
Exp/Cntr=0.3,0.1

Type RM Length L Ch R = 1 ,3437.7  ,426.3,434.2,441.8
XS GIS Cut Line= 4
     1892213.936      689210.523     1892161.852      688705.314
     1892196.032      688497.632     1892328.519      688080.314
#Sta/Elev= 30
       0  805.49    48.8   796.4    87.9  784.04   107.4  775.59   156.3  750.05
   205.1  723.65   253.9  695.82   263.7  691.25   273.5  687.99   332.1  673.86
   371.2  666.86     459  668.61   603.6  667.42   613.1  666.12   622.7  666.22
   625.6 667.504   632.3  670.47   651.4  685.56   680.1  705.77   699.2  722.59
   708.8  729.09   718.4   734.2   747.6  753.21   757.3  758.09   776.7  765.32
   825.4  781.25   922.7  808.18  1058.9  831.91  1107.6  838.47  1156.2  850.69
#Mann= 3 , 0 , 0
       0     .06       0   603.6    .045       0   625.6      .1       0
Bank Sta=603.6,625.6
XS Rating Curve= 0 ,0
Exp/Cntr=0.3,0.1

Type RM Length L Ch R = 1 ,3003.6  ,523.1,522.5,521.9
XS GIS Cut Line= 4
     1892362.373      689286.043     1892523.831      688871.981
     1892607.165      688720.939     1892745.186      688510.002
#Sta/Elev= 30
       0  765.17    77.3  742.26    96.6  735.47   125.6  724.19   183.6  705.51
   241.5  685.96   270.5  680.78   309.2  675.48   318.8  673.62   338.2  666.46
   347.8  664.05   376.8  663.06   482.8  662.59   492.4  661.85   501.9  660.23
   511.5  658.63   521.1  658.72   530.7   660.8   549.8  667.58   559.4  671.83
     569  677.16   578.6  683.71   588.2  691.27   607.4  707.56   616.9  714.98
   636.3  728.29   665.4  746.11   762.4  802.38   801.2  829.22     869  874.67
#Mann= 3 , 0 , 0
       0     .07       0   501.9    .045       0   530.7      .1       0
Bank Sta=501.9,530.7
XS Rating Curve= 0 ,0
Exp/Cntr=0.3,0.1

Type RM Length L Ch R = 1 ,2481.1  ,454.5,442.5,430.6
XS GIS Cut Line= 4
     1892786.852       689452.71     1892896.227      689226.148
     1892976.956      689072.502     1893148.831       688733.96
#Sta/Elev= 30
       0  781.78    19.4  775.35    38.7  767.94    58.1  759.65    77.4  750.49
   125.8  725.02   164.5  701.74   183.8  692.44   203.2  686.81   212.9  683.22
   270.9  659.87   280.5  657.61   309.4  658.34   328.7  656.43   338.4  654.93
     348  654.51   367.3  657.07   386.6  658.07   444.6  658.14   464.1  658.79
   473.8  660.77   483.6  664.67   590.6  718.47   619.8  731.52   668.5   751.9
   697.7  766.58   717.2  778.58   746.4  800.08   765.9  813.64   804.8  838.02
#Mann= 3 , 0 , 0
       0     .07       0   328.7    .045       0   367.3     .06       0
Bank Sta=328.7,367.3
XS Rating Curve= 0 ,0
Exp/Cntr=0.3,0.1

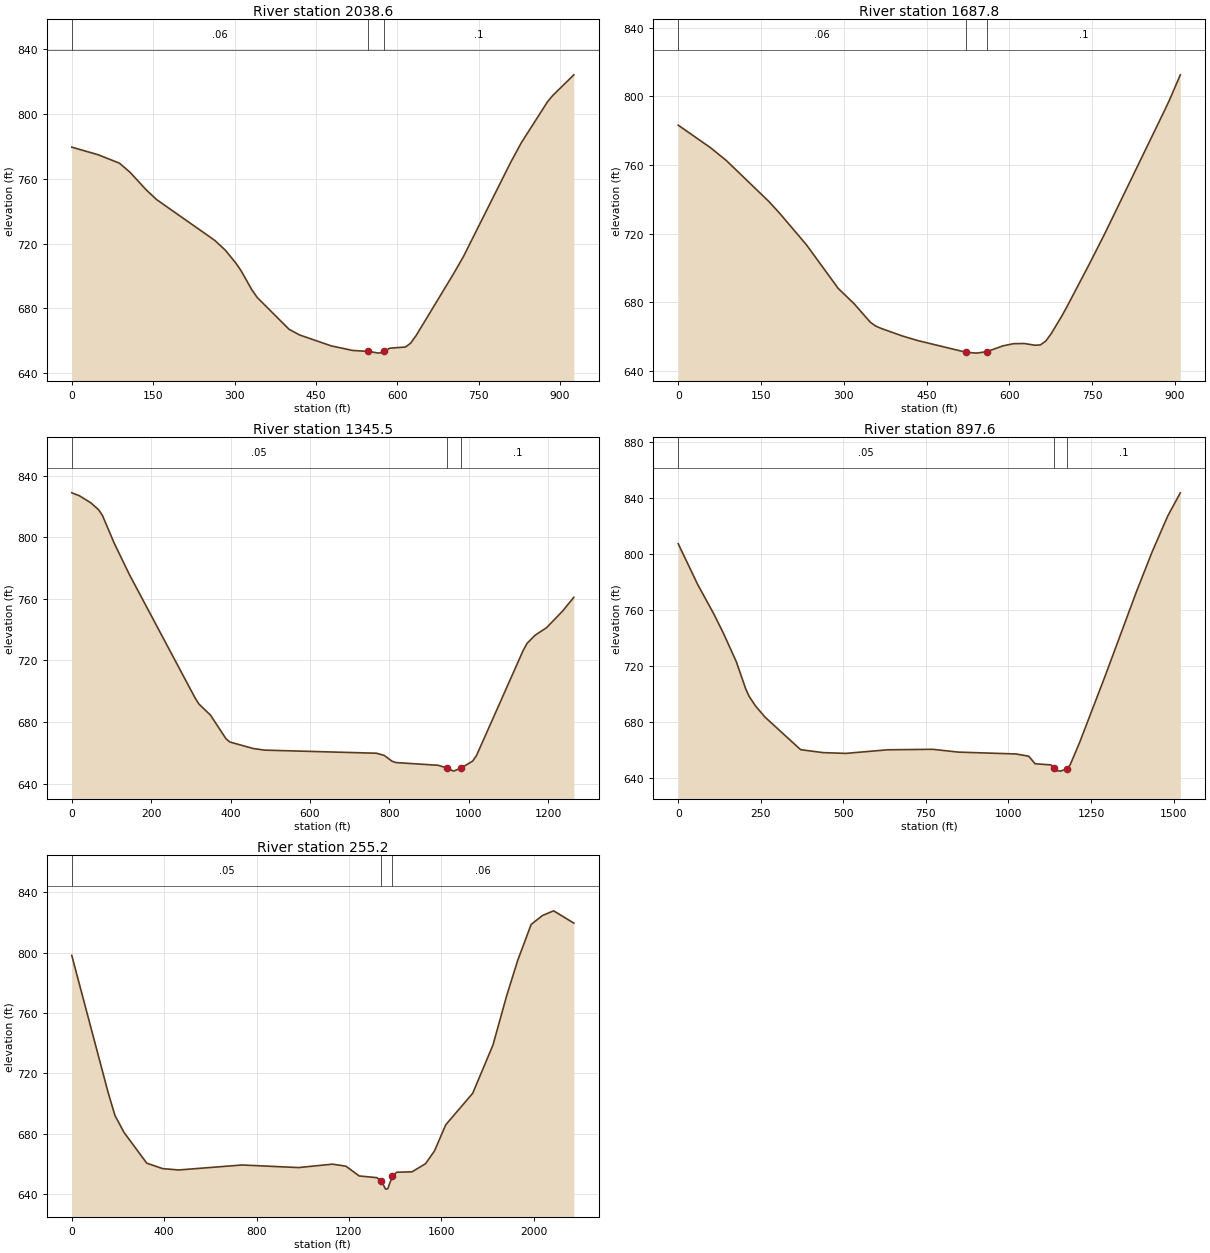
Type RM Length L Ch R = 1 ,2038.6  ,355.1,350.8,345.6
XS GIS Cut Line= 4
     1893370.186      689679.273     1893350.341      689181.612
     1893341.757      689064.865     1893333.727      688754.793
#Sta/Elev= 30
       0  779.55    48.8  774.85    87.9  769.64   107.4  764.03   136.7  753.34
   156.2  747.19   263.7  721.89   283.2  715.81   302.7  707.75   312.5  702.91
     332  691.34   341.8  686.63   400.4     667   419.9  663.46   478.5  656.69
   517.6   653.9   546.8  653.29   566.3  652.24   576.1  653.36   585.8  655.28
   615.1  656.02   624.8  658.48   634.5  663.04   702.4  700.61   721.7  711.84
     809  770.22   828.4  782.21   876.8  807.62   886.5   811.5   925.3  824.26
#Mann= 3 , 0 , 0
       0     .06       0   546.8    .045       0   576.1      .1       0
Bank Sta=546.8,576.1
XS Rating Curve= 0 ,0
Exp/Cntr=0.3,0.1

Type RM Length L Ch R = 1 ,1687.8  ,347.3,342.3,337.4
XS GIS Cut Line= 4
     1893743.883      689613.734     1893715.563      689179.634
     1893671.292      689012.968     1893585.029      688723.109
#Sta/Elev= 30
       0  783.23      58  770.21      87  762.67   164.3  738.69   183.7  731.88
     232  713.59     290  687.98     319  678.98     348   668.3   357.7  666.06
   367.4  664.69     406  660.26     435  657.49   521.2  650.78   540.4  650.24
   559.6  651.12   588.3  654.47   607.5  655.75     627  655.86   646.5  654.84
   656.2  655.03     666  657.24   675.8  661.55   695.3  671.96     705  677.65
     744  701.57   773.3  720.13   880.6  791.32   890.4     798   909.9  812.61
#Mann= 3 , 0 , 0
       0     .06       0   521.2    .045       0   559.6      .1       0
Bank Sta=521.2,559.6
XS Rating Curve= 0 ,0
Exp/Cntr=0.3,0.1

Type RM Length L Ch R = 1 ,1345.5  ,436.9,447.9,458.8
XS GIS Cut Line= 5
     1894072.008      689780.401     1894033.271      689189.617
     1893976.848      688942.221     1893892.212      688779.461
     1893767.321       688579.88
#Sta/Elev= 30
       0   828.8    19.4  826.88    48.5  822.22    67.9  817.74    77.6  813.94
   106.8  796.17   145.6  775.52   310.6  695.62   320.3  691.67   349.4  684.45
   388.2  669.25   397.9  667.04   456.2  662.83   485.3  661.74   767.7  659.72
   787.2   658.3   806.8  654.52   816.5  653.67     923  651.89   944.7  650.19
   961.7   648.1     981  650.15  1009.9  654.64  1019.6  658.29  1137.2  726.53
    1147  731.09  1166.6  736.24    1196  741.26  1235.3  751.72  1264.7  760.99
#Mann= 3 , 0 , 0
       0     .05       0   944.7    .045       0     981      .1       0
Bank Sta=944.7,981
XS Rating Curve= 0 ,0
Exp/Cntr=0.3,0.1

Type RM Length L Ch R = 1 ,897.6   ,629.7,642.5,655.4
XS GIS Cut Line= 4
     1894204.821      689801.234     1894298.571      688879.359
     1894298.571      688493.943     1894251.696      688290.818
#Sta/Elev= 30
       0  807.52    58.5  778.56   107.3  757.51   136.6  743.62   175.6   723.3
   204.8  703.45   214.6   698.4   234.1  691.45   263.4  683.36   370.6  660.22
   438.9  658.09   507.2  657.55     634  660.12   770.6  660.47   848.6  658.46
    1023  657.14  1061.5  655.53  1080.8  650.14    1129   649.3  1138.6  647.18
  1148.2  645.12  1157.9  644.86  1177.2  646.59  1186.8  649.29  1215.7  665.44
  1292.8  712.87  1387.8   773.3  1435.2  801.73  1482.6  827.46  1520.5  843.94
#Mann= 3 , 0 , 0
       0     .05       0  1138.6    .045       0  1177.2      .1       0
Bank Sta=1138.6,1177.2
XS Rating Curve= 0 ,0
Exp/Cntr=0.3,0.1

Type RM Length L Ch R = 1 ,255.2   ,251.5,255.2,258.1
XS GIS Cut Line= 5
     1894233.467      689811.651     1894538.154      689053.838
     1894835.029      688816.859     1894986.071      688585.088
     1894697.008      687947.068
#Sta/Elev= 30
       0  798.11   157.4   707.3     187  692.05   226.3  680.81   324.7  660.45
   393.6  656.84   462.5  655.94     738  659.25   982.4  657.53  1128.4   659.8
  1186.9  658.46  1244.3  651.99  1320.6  650.84  1339.7  648.75  1358.8  643.25
  1368.3  643.54  1387.4  651.62  1406.5  654.44  1473.3  654.74  1531.6   660.1
  1570.6  668.61  1619.2   685.9  1735.9  706.78  1823.5  738.73  1881.9  770.89
  1930.5  794.74  1988.9  818.64  2037.5  824.53  2086.2  827.66  2173.7  819.51
#Mann= 3 , 0 , 0
       0     .05       0  1339.7    .045       0  1387.4     .06       0
Bank Sta=1339.7,1387.4
XS Rating Curve= 0 ,0
Exp/Cntr=0.3,0.1

Chan Stop Cuts=-1
Use User Specified Reach Order=0
Composite Channel Slope=5